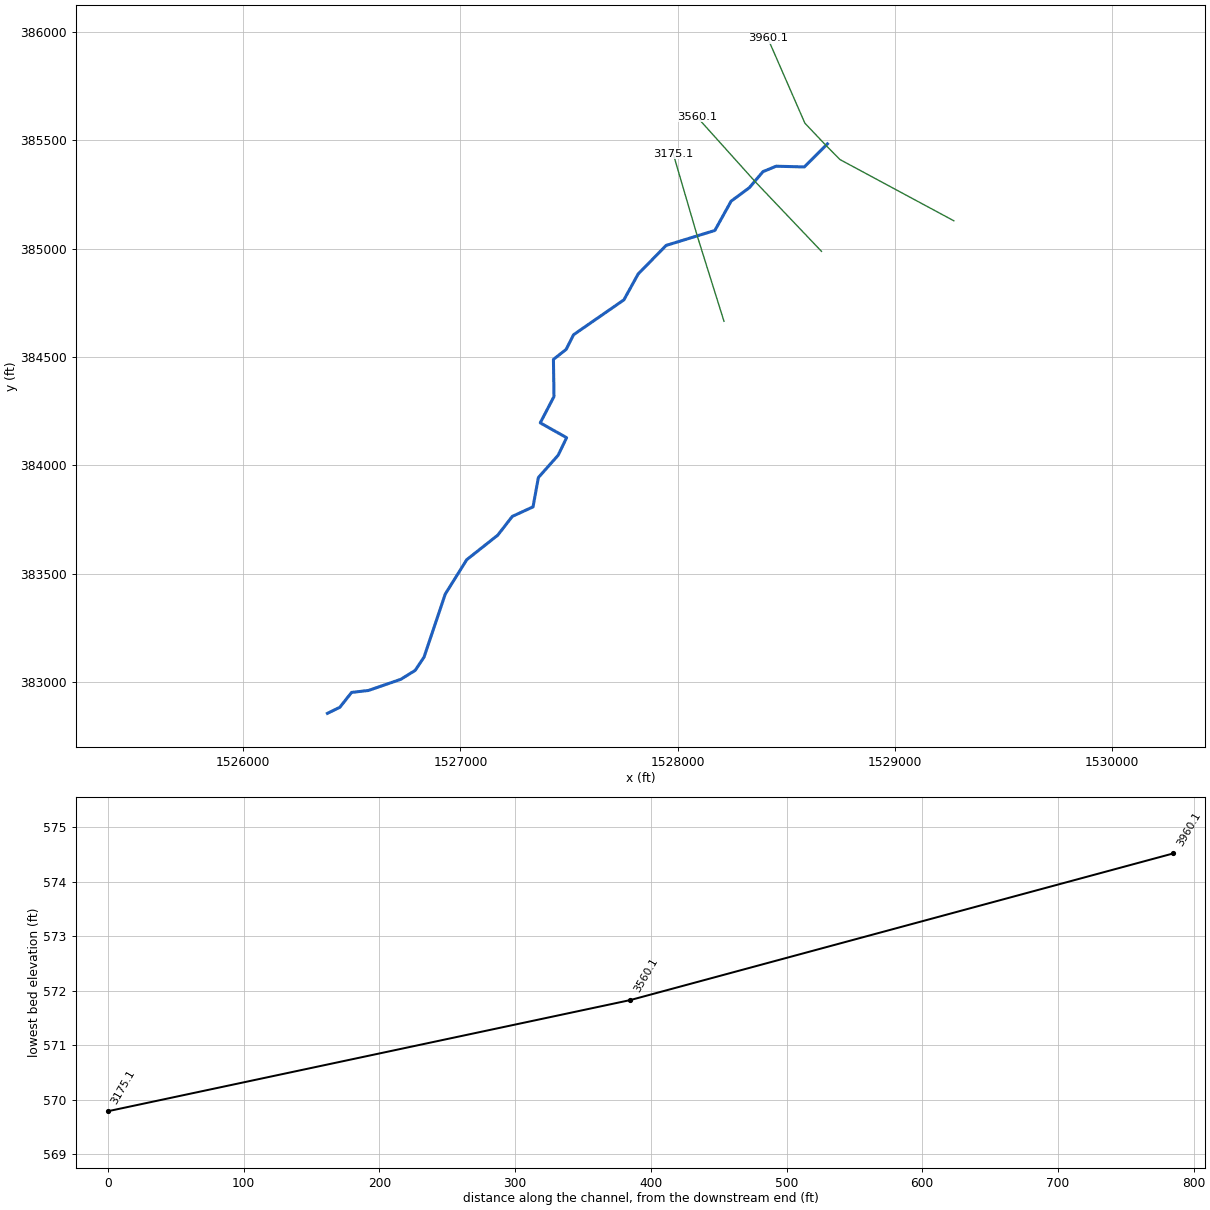
--- PWDRMILBR.prj (project) ---

Proj Title=PWDRMILBR
Current Plan=p01
Default Exp/Contr=0,0
English Units
Geom File=g01
Flow File=f01
Plan File=p01
BEGIN DESCRIPTION:
END DESCRIPTION:
DSS Export Rating Curves= 0
DSS Export Rating Curve Sorted= 0
DSS Export Volume Flow Curves= 0
DXF OffsetX= 0
DXF OffsetY= 0
DXF ScaleX= 0
DXF ScaleY= 0

--- PWDRMILBR.p01 (plan) ---

Plan Title=Floodplain
Program Version=4.00
Geom File=g01
Flow File=f01
K Sum by GR=0
Std Step Tol=0.01
Critical Tol=0.01
Num of Std Step Trials=20
Max Error Tol=0.3
Flow Tol Ratio=0.001
Split Flow NTrial=30
Split Flow Tol=0.02
Split Flow Ratio=0.02
Log Output Level=0
Friction Slope Method=1
Unsteady Friction Slope Method=2
Unsteady Bridges Friction Slope Method=1
Global Log Level=0
CheckData=False
Run HTab=0
Run UNet=0
Run PostProcess=0
UNET Theta=0
UNET Theta Warmup=0
UNET ZTol=0
UNET ZSATol=0
UNET MxIter=0
UNET MaxInSteps=0
UNET DtIC=0
UNET DtMin=0
UNET MaxCRTS=0
UNET WFStab=0
UNET SFStab=0
UNET WFX=0
UNET SFX=0
UNET DSS MLevel=0
UNET DZMax Abort=0
UNET Convert EG Bridges=0
UNET Use Existing IB Tables=0
UNET Froude Limit=0
UNET Froude Power=0
Write IC File=0
Echo Input=False
Echo Output=False
Write Detailed=0

--- PWDRMILBR.f01 (steady flow) ---

Flow Title=NFF Regression Equation
Program Version=4.00
Number of Profiles=1
Profile Names=P100yr
River Rch & RM=PWDRMILBR,Main      ,3960.1
     366
Boundary for River Rch & Prof#=PWDRMILBR,Main      ,1
Up Type=0
Dn Type=3
Dn Slope=0.006012

--- PWDRMILBR.g01 (geometry) ---

Geom Title=USGS 10m DEM
Program Version=4.00

River Reach=PWDRMILBR     ,Main
Reach XY= 30
     1528689.984      385482.873     1528583.561      385376.383
     1528453.554      385379.748     1528393.035      385354.738
     1528330.061      385280.439     1528246.387      385218.569
     1528171.398      385083.234     1527946.968      385014.287
     1527818.102      384882.223     1527752.501      384763.035
     1527520.705      384602.025     1527486.566      384534.516
     1527428.009      384488.169     1527430.587      384316.998
     1527367.310      384195.453     1527488.812      384127.020
     1527449.618      384045.858     1527358.698      383943.207
     1527334.057      383807.836     1527238.504      383763.749
     1527171.554      383677.185     1527028.502      383563.737
     1526929.798      383405.231     1526832.091      383114.471
     1526791.487      383053.359     1526725.576      383012.202
     1526576.203      382960.583     1526498.510      382951.552
     1526444.261      382882.852     1526387.113      382854.860

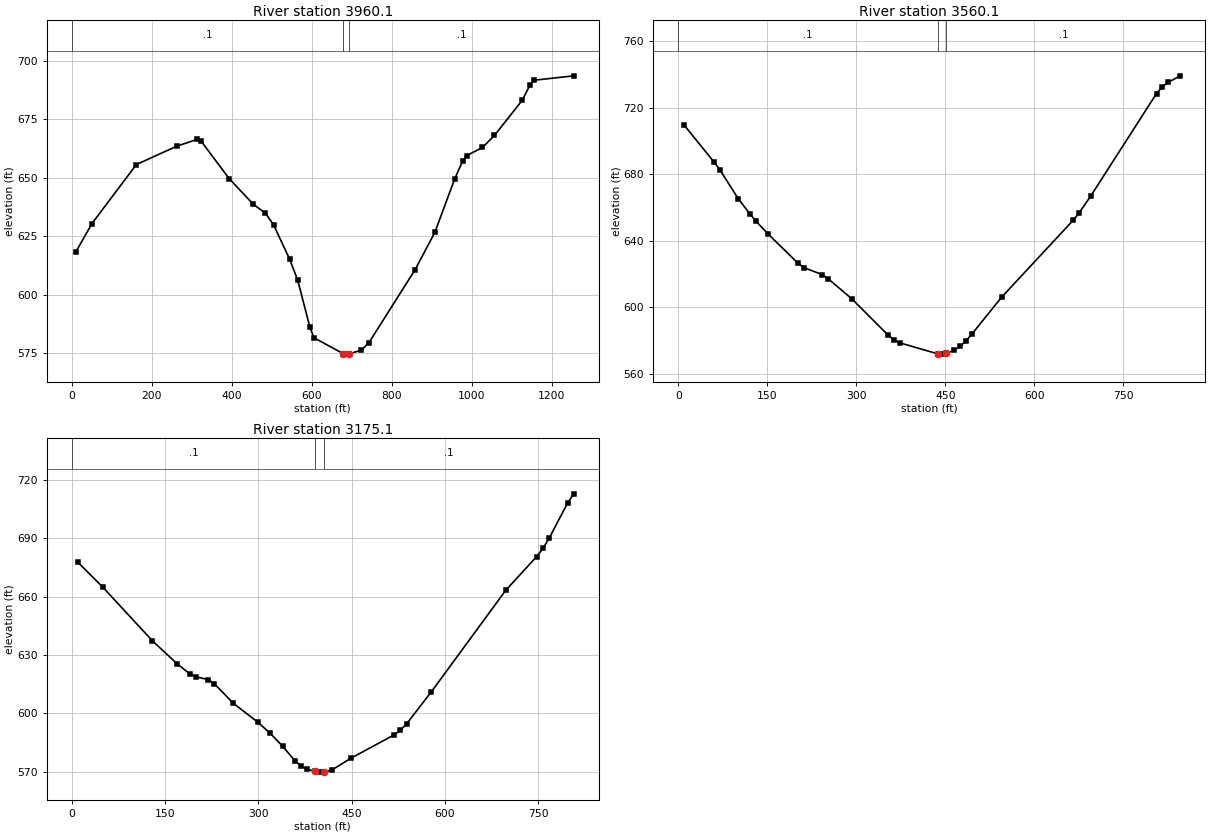
Type RM Length L Ch R = 1 ,3960.1,400.4,400,399.5
XS GIS Cut Line= 5
     1529271.895      385127.975     1528747.729      385410.394
     1528683.976      385474.879     1528586.034      385578.348
     1528415.304      385969.849
#Sta/Elev= 30
    10.1  618.18    50.5  630.37   161.5  655.58   262.4  663.42   312.8  666.30
   322.9  665.72   393.6  649.59   454.1  638.57   484.4  634.79   504.6  629.85
   545.0  615.08   565.1  606.12   595.4  586.13   605.5  581.53   678.6  574.75
   686.1  574.52   693.6  574.65   724.1  576.21   743.1  579.39   858.4  610.55
   908.0  626.55   957.7  649.45   977.6  657.04   987.5  659.39  1027.2  662.88
  1057.0  668.01  1126.5  683.01  1146.4  689.72  1156.3  691.64  1255.7  693.52
#Mann= 3 , 0 , 0
       0     0.1       0   678.6   0.045       0   693.6     0.1       0
Bank Sta=   678.6,   693.6
Exp/Cntr=0.3,0.1

Type RM Length L Ch R = 1 ,3560.1,395.4,385,374.9
XS GIS Cut Line= 3
     1528662.568      384986.682     1528356.631      385309.004
     1528088.563      385607.784
#Sta/Elev= 30
    10.1  709.48    60.6  687.22    70.7  682.37   101.0  665.34   121.2  655.91
   131.3  651.66   151.5  644.04   202.0  626.41   212.1  623.83   242.4  619.66
   252.5  617.20   292.9  604.93   353.5  583.29   363.6  580.42   373.7  578.58
   436.9  572.02   444.4  571.83   451.9  572.33   464.5  574.11   474.5  576.43
   484.5  579.69   494.6  583.84   544.7  606.04   665.2  652.28   675.2  656.68
   695.3  667.13   805.7  728.54   815.7  732.73   825.7  735.35   845.8  739.19
#Mann= 3 , 0 , 0
       0     0.1       0   436.9   0.045       0   451.9     0.1       0
Bank Sta=   436.9,   451.9
Exp/Cntr=0.3,0.1

Type RM Length L Ch R = 1 ,3175.1,3175.9,3175.1,3172.1
XS GIS Cut Line= 3
     1528213.498      384664.185     1528091.507      385054.385
     1527979.649      385437.055
#Sta/Elev= 30
    10.0  677.59    49.9  664.84   129.6  637.29   169.5  625.43   189.5  620.39
   199.4  618.78   219.4  617.35   229.3  615.23   259.3  605.31   299.1  595.46
   319.1  589.78   339.0  583.13   359.0  575.59   368.9  572.84   378.9  571.22
   391.4  570.18   398.9  569.79   406.4  569.85   418.8  570.96   448.7  576.90
   518.5  588.93   528.4  591.25   538.4  594.56   578.3  611.05   697.9  663.19
   747.7  680.54   757.7  684.71   767.6  689.85   797.5  708.10   807.5  712.79
#Mann= 3 , 0 , 0
       0     0.1       0   391.4   0.045       0   406.4     0.1       0
Bank Sta=   391.4,   406.4
Exp/Cntr=0.3,0.1